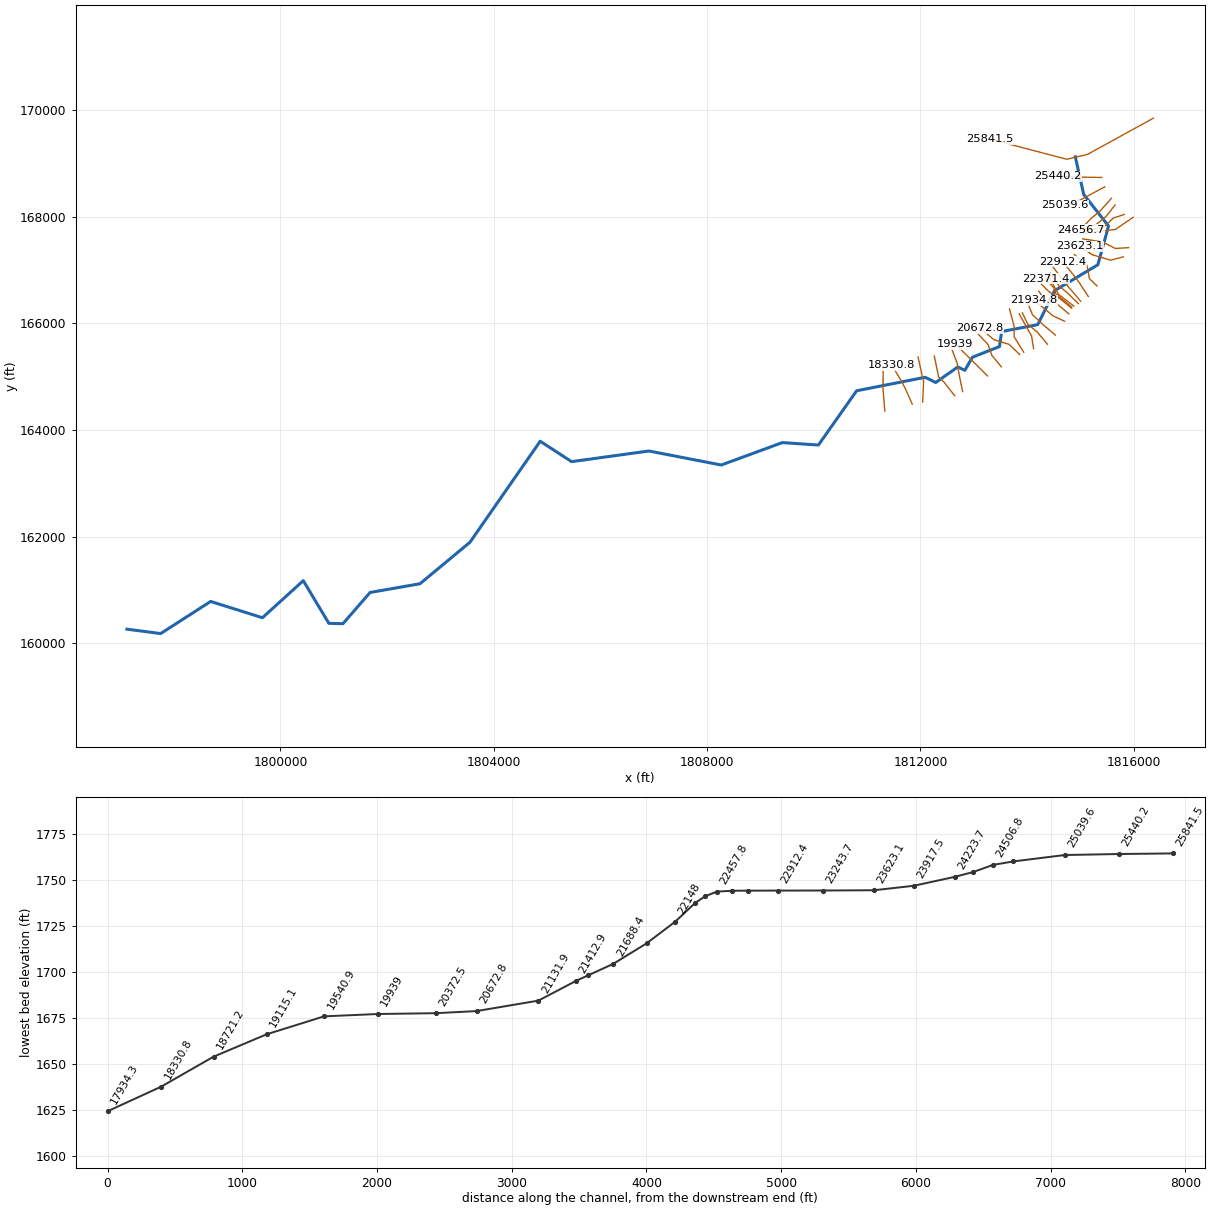
--- Browns Creek.prj (project) ---

Proj Title=Browns Creek
Current Plan=p01
Default Exp/Contr=0,0
English Units
Geom File=g01
Flow File=f01
Plan File=p01
BEGIN DESCRIPTION:
END DESCRIPTION:
DSS Export Rating Curves= 0
DSS Export Rating Curve Sorted= 0
DSS Export Volume Flow Curves= 0
DXF OffsetX= 0
DXF OffsetY= 0
DXF ScaleX= 0
DXF ScaleY= 0

--- Browns Creek.p01 (plan) ---

Plan Title=Floodplain
Program Version=4.00
Geom File=g01
Flow File=f01
K Sum by GR=0
Std Step Tol=0.01
Critical Tol=0.01
Num of Std Step Trials=20
Max Error Tol=0.3
Flow Tol Ratio=0.001
Split Flow NTrial=30
Split Flow Tol=0.02
Split Flow Ratio=0.02
Log Output Level=0
Friction Slope Method=1
Unsteady Friction Slope Method=2
Unsteady Bridges Friction Slope Method=1
Global Log Level=0
CheckData=False
Run HTab=0
Run UNet=0
Run PostProcess=0
UNET Theta=0
UNET Theta Warmup=0
UNET ZTol=0
UNET ZSATol=0
UNET MxIter=0
UNET MaxInSteps=0
UNET DtIC=0
UNET DtMin=0
UNET MaxCRTS=0
UNET WFStab=0
UNET SFStab=0
UNET WFX=0
UNET SFX=0
UNET DSS MLevel=0
UNET DZMax Abort=0
UNET Convert EG Bridges=0
UNET Use Existing IB Tables=0
UNET Froude Limit=0
UNET Froude Power=0
Write IC File=0
Echo Input=False
Echo Output=False
Write Detailed=0

--- Browns Creek.f01 (steady flow) ---

Flow Title=NFF Regression Equation
Program Version=4.00
Number of Profiles=1
Profile Names=P100yr
River Rch & RM=Browns Creek,Main      ,25841.5
558.1632
River Rch & RM=Browns Creek,Main      ,24223.7
598.6050
River Rch & RM=Browns Creek,Main      ,23917.5
767.3636
River Rch & RM=Browns Creek,Main      ,20672.8
845.2538
River Rch & RM=Browns Creek,Main      ,20372.5
982.1868
River Rch & RM=Browns Creek,Main      ,17671.1
1042.201
River Rch & RM=Browns Creek,Main      ,17384.1
1534.238
River Rch & RM=Browns Creek,Main      ,14976.2
1658.905
Boundary for River Rch & Prof#=Browns Creek,Main      ,1
Up Type=0
Dn Type=3
Dn Slope=0.025815

--- Browns Creek.g01 (geometry) ---

Geom Title=USGS 10m DEM
Program Version=4.00

River Reach=Browns Creek    ,Main
Reach XY= 30
     1814905.513      169118.269      1815063.64      168412.302
     1815528.135      167822.654     1815328.226      167096.092
     1814517.036      166611.523     1814200.166      165973.912
     1813524.002      165844.558     1813482.844      165563.174
     1812974.671      165363.264      1812835.27       165118.18
     1812701.686      165180.994     1812287.588      164890.369
     1812089.358      164987.804     1810805.135      164735.532
     1810087.957      163718.656     1809411.292      163764.324
     1808267.008      163344.303     1806909.819      163606.736
     1805460.006      163407.338     1804870.819      163789.409
     1803554.153      161897.063     1802616.985      161119.413
     1801681.167      160956.015     1801172.353      160370.988
     1800908.147      160377.521     1800428.368      161177.396
     1799663.172      160482.744     1798691.434       160787.62
     1797754.375      160185.899     1797122.925      160268.217

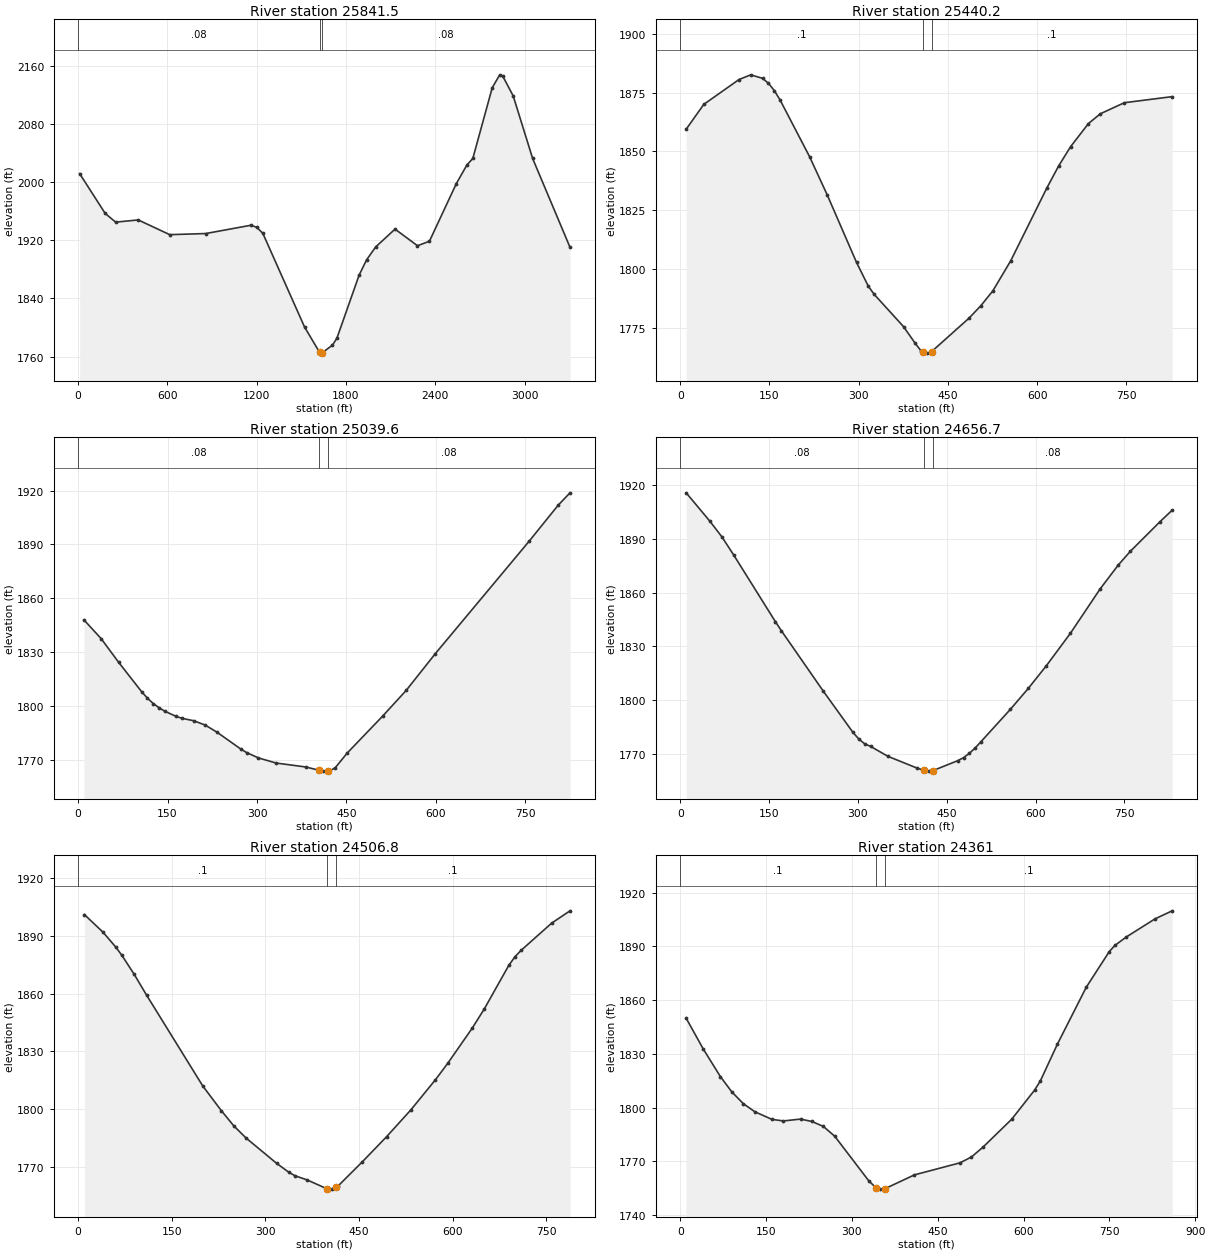
Type RM Length L Ch R = 1 ,25841.5 ,406.6,401.3,395.2
XS GIS Cut Line= 4
     1816370.776      169843.515      1815132.18      169163.499
     1814747.514      169072.989     1813298.513      169452.144
#Sta/Elev= 30
    10.1 2011.47   181.7 1956.81   252.3 1944.77   403.7 1947.81   615.7 1927.56
   857.9 1929.11  1160.7  1940.5    1201 1937.66  1241.4 1929.34  1521.7  1800.6
  1622.8 1765.71  1630.3 1764.68  1637.8 1764.69  1709.4 1775.76    1739 1785.12
  1888.6 1872.04  1938.8 1892.97  1999.2 1910.55  2129.8  1935.2  2280.6 1912.35
    2361 1918.52    2542 1997.83  2612.3 2023.17  2652.6 2032.38  2783.2 2129.66
  2833.5 2147.33  2853.6  2145.6    2924 2118.33  3054.6 2032.31  3305.9 1910.14
#Mann= 3 , 0 , 0
       0     .08       0  1622.8    .045       0  1637.8     .08       0
Bank Sta=1622.8,1637.8
XS Rating Curve= 0 ,0
Exp/Cntr=0.3,0.1

Type RM Length L Ch R = 1 ,25440.2 ,388.8,400.6,413.1
XS GIS Cut Line= 3
      1815404.07      168732.592     1814989.216      168737.982
     1814577.506      168756.502
#Sta/Elev= 30
     9.9 1859.41    39.5 1869.96    98.8 1880.52   118.5 1882.51   138.3 1881.02
   148.2 1878.94   158.1 1875.83   167.9 1871.78   217.3 1847.81     247 1831.57
   296.3 1802.89   316.1 1792.79     326 1789.31   375.4 1775.59   395.1 1768.48
     405 1765.23   407.4 1765.02   414.9 1764.35   422.4 1764.96   485.3 1779.16
   505.4 1784.49   525.5 1790.79   555.6 1803.57   615.9 1834.26     636 1843.76
   656.1 1851.96   686.3 1861.84   706.4 1865.99   746.6 1870.67     827 1873.25
#Mann= 3 , 0 , 0
       0      .1       0   407.4    .045       0   422.4      .1       0
Bank Sta=407.4,422.4
XS Rating Curve= 0 ,0
Exp/Cntr=0.3,0.1

Type RM Length L Ch R = 1 ,25039.6 ,378.8,383,387.2
XS GIS Cut Line= 4
     1815456.846       168555.88     1815260.256      168450.798
     1814980.802      168300.381     1814709.552      168213.939
#Sta/Elev= 30
     9.7 1848.03    38.8 1837.49    67.8 1824.45   106.6 1807.98   116.3 1804.39
     126 1801.43   135.7 1799.12   145.4 1797.14   164.8 1794.22   174.5 1793.19
   193.8 1791.86   213.2 1789.43   232.8  1785.5   272.5 1776.17   282.4 1774.17
   302.3 1771.15     332 1768.31   381.6 1766.12   403.8 1764.31   411.3  1763.8
   418.8 1763.83   421.3 1763.84   431.2 1765.66     451 1773.77   510.5 1794.35
   550.1  1808.7   599.2 1829.27   756.2 1891.73   805.3 1911.94     825 1918.76
#Mann= 3 , 0 , 0
       0     .08       0   403.8    .045       0   418.8     .08       0
Bank Sta=403.8,418.8
XS Rating Curve= 0 ,0
Exp/Cntr=0.3,0.1

Type RM Length L Ch R = 1 ,24656.7 ,149.8,149.9,150
XS GIS Cut Line= 4
     1815582.667      168341.277     1815368.908       168101.33
     1815200.941      167965.436     1815000.522      167751.508
#Sta/Elev= 30
      10 1915.76    50.2 1899.82    70.3 1891.15    90.4 1880.94   160.7 1843.74
   170.7 1838.73     241 1805.21   291.2 1782.12   301.3 1778.29   311.3 1775.58
   321.4 1774.11   350.8 1768.54   399.9 1761.99   412.1 1760.69   419.6  1760.3
   427.1 1760.65   468.7 1766.16   478.5 1767.88   488.3 1770.28   498.1 1773.29
   507.9 1776.79   557.6 1794.89     588 1806.65   618.3 1819.23   658.7 1837.27
   709.3 1862.24   739.6 1875.42   759.8 1883.04   810.3 1899.71   830.6 1906.07
#Mann= 3 , 0 , 0
       0     .08       0   412.1    .045       0   427.1     .08       0
Bank Sta=412.1,427.1
XS Rating Curve= 0 ,0
Exp/Cntr=0.3,0.1

Type RM Length L Ch R = 1 ,24506.8 ,144.7,145.7,146.8
XS GIS Cut Line= 4
     1815651.077      168216.763     1815484.926      168004.778
     1815295.857      167850.085     1815039.947      167750.777
#Sta/Elev= 30
      10  1901.2    39.9 1892.01    59.9 1884.44    69.8 1880.13    89.8 1870.14
   109.7 1859.28   199.5 1812.14   229.4 1799.23   249.4 1791.31   269.3 1784.92
   318.2 1771.77   337.7 1767.17   347.5 1765.36   367.1 1763.17   398.6 1758.61
   406.1 1758.41   413.6 1759.53   415.9 1759.87     455 1772.51   494.1 1785.65
   533.2 1799.66   572.5 1815.31   592.1  1823.8   631.3 1842.08   650.9 1852.21
   690.1 1874.84   699.9 1879.26   709.7 1882.59   758.7 1896.75   788.1 1903.14
#Mann= 3 , 0 , 0
       0      .1       0   398.6    .045       0   413.6      .1       0
Bank Sta=398.6,413.6
XS Rating Curve= 0 ,0
Exp/Cntr=0.3,0.1

Type RM Length L Ch R = 1 ,24361   ,151.8,137.4,123
XS GIS Cut Line= 4
     1815821.894      168038.275      1815621.71      167973.868
     1815423.267      167792.832     1815047.586      167729.769
#Sta/Elev= 30
      10 1850.14    40.1 1832.82    70.1  1817.4    90.1 1808.84   110.2 1802.27
   130.2 1797.79   160.2  1793.5   180.2 1792.63   210.3 1793.66   230.2 1792.32
   250.1 1789.57     270 1784.09   329.7 1759.11   342.1 1755.37   349.6 1754.57
   357.1 1754.71   409.3 1762.53   488.9 1769.24     509 1772.51     529 1777.97
   579.2 1793.55   619.2 1809.76   629.3 1814.91   659.3 1835.56   709.5 1867.17
   749.6 1887.03   759.6 1890.57   779.6 1895.29   829.8 1905.41   859.8  1909.9
#Mann= 3 , 0 , 0
       0      .1       0   342.1    .045       0   357.1      .1       0
Bank Sta=342.1,357.1
XS Rating Curve= 0 ,0
Exp/Cntr=0.3,0.1

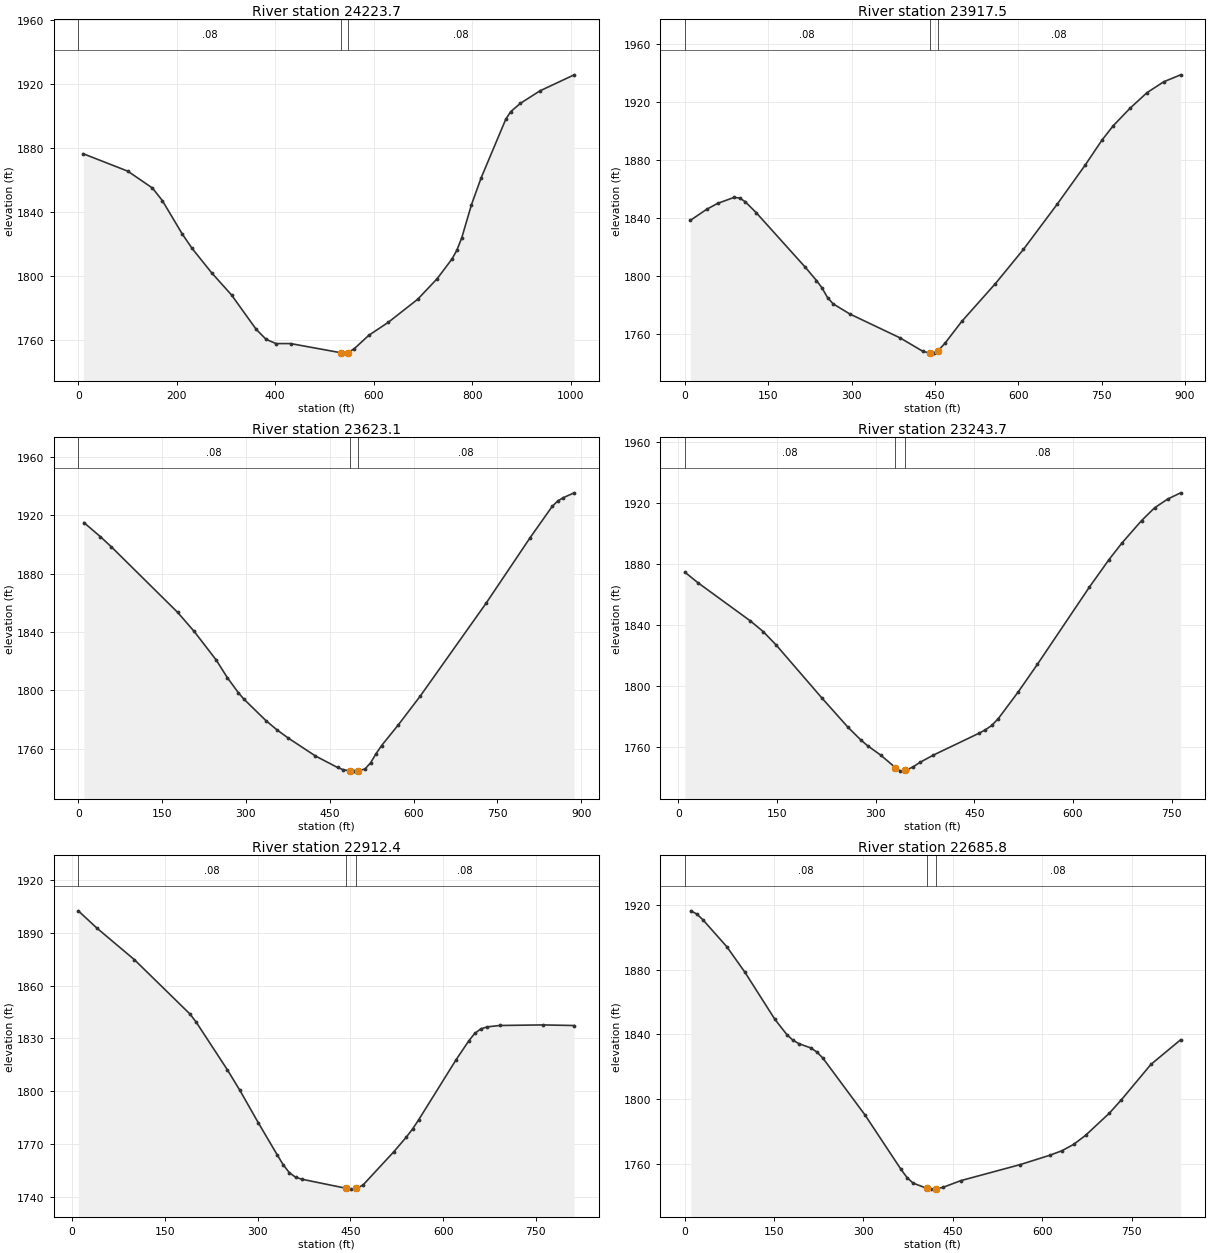
Type RM Length L Ch R = 1 ,24223.7 ,319.8,306.2,291.8
XS GIS Cut Line= 4
     1815989.108       167983.77     1815656.806      167758.416
     1815410.444      167727.859     1815056.007      167680.774
#Sta/Elev= 30
      10 1876.56   100.4 1865.68   150.6 1855.12   170.6 1847.31   210.8 1826.56
   230.9 1817.46     271 1802.08   311.2 1788.29   361.4 1766.75   381.4 1760.56
   401.5 1757.89   431.3 1757.88     533 1752.17   540.5 1751.91     548  1752.3
   560.4 1754.62   590.2 1763.08   629.9 1771.22   689.5 1785.61   729.2 1798.53
     759 1810.73   768.9 1816.17   778.9 1823.97   798.7 1844.73   818.6  1861.7
   868.3 1898.09   878.2 1902.82   898.1 1908.09   937.8 1915.88  1007.3  1925.9
#Mann= 3 , 0 , 0
       0     .08       0     533    .045       0     548     .08       0
Bank Sta=533,548
XS Rating Curve= 0 ,0
Exp/Cntr=0.3,0.1

Type RM Length L Ch R = 1 ,23917.5 ,290.5,294.4,298.7
XS GIS Cut Line= 4
     1815903.168      167416.565     1815656.806      167401.287
     1815414.264      167523.513     1815045.058      167582.276
#Sta/Elev= 30
     9.9 1838.52    39.5  1846.2    59.2 1850.26    88.9 1854.39    98.7 1853.91
   108.6 1851.45   128.4 1843.89   217.2 1806.08     237 1797.05   246.8 1792.07
   256.9  1785.3     267 1780.98   297.1 1773.99   387.7 1757.48   427.9 1748.37
   440.5 1747.04     448 1747.02   455.5 1748.58   468.1 1753.76   498.3 1768.83
   558.9 1794.92   609.4 1818.53     670  1849.6   720.5 1876.62   750.8 1893.87
     771 1903.76   801.3 1915.84   831.7 1926.54     862 1934.09   892.3 1938.86
#Mann= 3 , 0 , 0
       0     .08       0   440.5    .045       0   455.5     .08       0
Bank Sta=440.5,455.5
XS Rating Curve= 0 ,0
Exp/Cntr=0.3,0.1

Type RM Length L Ch R = 1 ,23623.1 ,405.1,379.3,353.6
XS GIS Cut Line= 4
     1815803.859      167244.685     1815565.137      167181.662
     1815215.647        167286.7     1814990.292      167445.212
#Sta/Elev= 30
     9.9 1915.09    39.5 1905.39    59.3 1898.36   177.8 1853.47   207.4 1840.38
   246.9 1820.73   266.6 1808.77   286.4 1798.38   296.2 1794.03   335.7 1779.27
   355.4 1772.94   375.1 1767.44   424.4 1754.99   463.9  1747.1   473.8 1745.62
     486 1744.76   493.5  1744.6     501 1744.69   513.2 1746.13   523.1 1750.33
   532.9  1756.6   542.8 1762.15   572.4 1776.19   611.8 1795.99   729.9 1859.82
   808.6  1904.7     848 1926.11   857.8 1929.79   867.7 1932.09   887.4 1935.46
#Mann= 3 , 0 , 0
       0     .08       0     486    .045       0     501     .08       0
Bank Sta=486,501
XS Rating Curve= 0 ,0
Exp/Cntr=0.3,0.1

Type RM Length L Ch R = 1 ,23243.7 ,317.5,331.3,342.4
XS GIS Cut Line= 4
     1815313.045      166698.487     1815169.812      166835.992
     1815125.887      167080.444     1814887.164       167288.61
#Sta/Elev= 30
     9.9 1874.74    29.8 1867.82   109.2 1842.91   129.1 1835.82   148.9 1826.98
   218.4  1792.3   258.2 1773.09     278 1764.67     288 1761.03   307.8 1754.92
   330.1 1746.77  337.57 1744.46   345.1 1745.21   347.6 1745.29   357.5  1747.4
   367.4 1750.19   387.3 1754.85   456.8 1769.18   466.7 1771.45   476.6 1774.38
   486.5 1778.85   516.2 1795.96   545.9 1814.35   625.1    1865   654.8 1882.94
   674.6 1893.85   704.3 1908.46   724.1 1916.82   743.9 1922.53   763.7 1926.64
#Mann= 3 , 0 , 0
     9.9     .08       0   330.1    .045       0   345.1     .08       0
Bank Sta=330.1,345.1
XS Rating Curve= 0 ,0
Exp/Cntr=0.3,0.1

Type RM Length L Ch R = 1 ,22912.4 ,225.8,226.6,226.3
XS GIS Cut Line= 4
     1815148.804       166501.78     1814973.104      166771.059
     1814852.788      166929.571      1814665.63      167153.015
#Sta/Elev= 30
      10 1902.46    40.2  1892.6   100.5 1874.78   190.9 1843.75     201 1839.06
   251.2 1812.11   271.3 1800.53   301.4 1781.92   331.5    1764   341.4 1758.25
   351.4 1753.71   361.3 1751.21   371.3 1750.07   443.4 1744.87   450.9 1744.42
   458.4 1744.82   460.8 1744.88   470.8 1746.87   520.5 1765.73   540.6 1773.99
   550.7 1778.61   560.7  1783.9     621 1817.89   641.1 1828.38   651.2 1832.88
   661.2 1835.44   671.3 1836.55   691.4 1837.35   761.8 1837.67     812 1837.33
#Mann= 3 , 0 , 0
      10     .08       0   443.4    .045       0   458.4     .08       0
Bank Sta=443.4,458.4
XS Rating Curve= 0 ,0
Exp/Cntr=0.3,0.1

Type RM Length L Ch R = 1 ,22685.8 ,109,113.6,119.4
XS GIS Cut Line= 3
     1815006.417      166411.324     1814732.508      166734.357
     1814484.404      167059.338
#Sta/Elev= 30
    10.1 1916.34    20.2 1914.35    30.3 1910.86    70.6 1894.14   100.8 1878.47
   151.3 1849.27   171.4 1839.83   181.5 1836.41   191.6 1834.27   211.8 1831.59
   221.8 1829.08   231.9  1825.3   302.5 1790.21     363 1756.57   373.1 1751.53
   383.2 1748.11   405.9 1744.93   413.4 1744.38   420.9 1744.42   433.5 1745.49
   463.4 1749.63   563.1 1759.54     613 1765.33   632.9 1768.07   652.9 1772.04
   672.8 1777.61   712.7  1791.3   732.7 1799.46   782.5 1821.43   832.4 1836.67
#Mann= 3 , 0 , 0
       0     .08       0   405.9    .045       0   420.9     .08       0
Bank Sta=405.9,420.9
XS Rating Curve= 0 ,0
Exp/Cntr=0.3,0.1

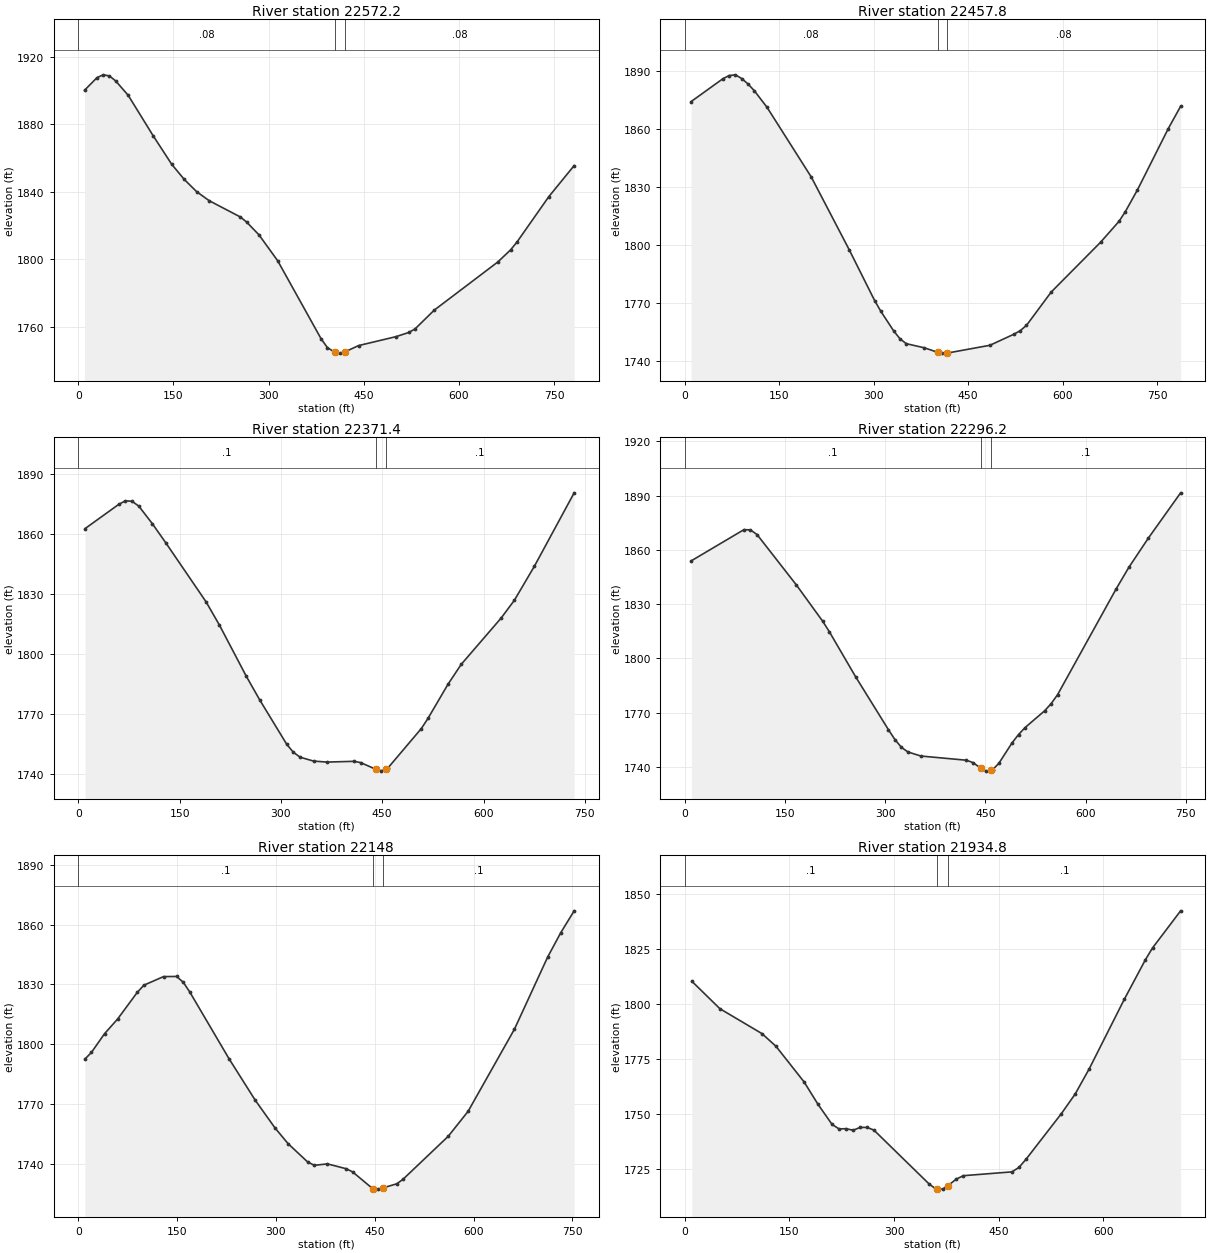
Type RM Length L Ch R = 1 ,22572.2 ,134.7,114.4,97.1
XS GIS Cut Line= 4
     1814961.975      166368.918     1814736.928      166588.382
     1814605.748      166690.914     1814434.534      166938.135
#Sta/Elev= 30
     9.8 1900.28    29.5 1907.78    39.3 1909.42    49.1 1908.75    58.9 1905.79
    78.6 1897.27   117.9 1873.31   147.3  1856.3     167 1847.37   186.6 1840.08
   206.3 1834.76   255.4  1825.1   265.2 1822.11   284.9 1814.44   314.3  1799.1
   382.9 1752.71   392.7 1747.59   404.8 1744.77   412.3 1744.34   419.8    1745
   441.7 1748.81   500.9 1754.13   520.9 1756.58     531 1758.77     561 1769.82
   661.3 1798.42   681.3 1805.55   691.3 1810.15   741.5 1837.09   781.6  1855.6
#Mann= 3 , 0 , 0
       0     .08       0   404.8    .045       0   419.8     .08       0
Bank Sta=404.8,419.8
XS Rating Curve= 0 ,0
Exp/Cntr=0.3,0.1

Type RM Length L Ch R = 1 ,22457.8 ,81,86.4,89.1
XS GIS Cut Line= 3
      1814875.87      166322.727     1814589.162      166543.148
     1814396.161      166892.962
#Sta/Elev= 30
      10 1874.08    60.3 1885.88    70.3 1887.56    80.4 1887.94    90.4 1886.01
   100.5 1883.17   110.5 1879.66   130.6  1871.1   200.9 1834.98   261.2 1797.28
   301.4 1771.08   311.4 1765.43   331.5 1755.43   341.6  1751.3   351.6 1748.76
   380.5  1746.6   401.4  1744.3   408.9 1743.86   416.4 1743.87   484.5 1747.93
     523 1753.73   532.7 1755.53   542.5 1758.24   581.7 1775.48     660 1801.23
   689.3 1812.05   699.1 1816.93   718.7  1828.4   767.6 1860.11   787.2 1871.65
#Mann= 3 , 0 , 0
       0     .08       0   401.4    .045       0   416.4     .08       0
Bank Sta=401.4,416.4
XS Rating Curve= 0 ,0
Exp/Cntr=0.3,0.1

Type RM Length L Ch R = 1 ,22371.4 ,59.2,75.2,90.7
XS GIS Cut Line= 4
     1814836.086      166303.761     1814538.978      166553.435
     1814500.201      166666.789     1814345.922      166832.411
#Sta/Elev= 30
      10 1862.86    59.7 1874.96    69.7 1876.78    79.6 1876.53    89.6 1874.09
   109.5 1865.36   129.4 1855.79   189.1  1826.2     209 1814.49   248.8 1788.84
   268.7 1776.99   308.5 1754.88   318.4 1750.84   328.4 1748.37   348.3 1746.42
   368.2 1745.92   408.1  1746.3     418 1745.67   440.5 1742.32     448 1741.39
   455.5 1742.45     458  1742.8   507.9 1762.71   517.7 1767.77   547.3 1784.86
   566.9 1794.83     626 1818.03   645.7 1826.97   675.2 1843.94   734.2 1880.77
#Mann= 3 , 0 , 0
       0      .1       0   440.5    .045       0   455.5      .1       0
Bank Sta=440.5,455.5
XS Rating Curve= 0 ,0
Exp/Cntr=0.3,0.1

Type RM Length L Ch R = 1 ,22296.2 ,135,148.2,161.4
XS GIS Cut Line= 4
      1814837.51      166284.065     1814607.476      166468.712
     1814409.719      166593.449     1814258.846      166744.322
#Sta/Elev= 30
     9.8 1853.98    88.5 1871.18    98.3 1871.05   108.2 1868.46   167.2 1840.53
   206.5 1820.52   216.3 1814.81   255.6 1789.94   304.7 1760.69   314.5 1755.19
   324.2  1750.9   333.9 1748.32   353.4 1746.07   421.6 1743.74   431.4 1742.43
   443.3 1739.28   450.8 1737.72   458.3 1738.26   460.6 1738.43   470.3 1742.12
   489.8  1753.3   499.6 1757.96   509.3 1761.77   538.5 1771.02   548.2 1774.94
   557.9 1779.91   645.2 1838.12   664.6  1850.3   693.7 1866.41   742.2 1891.54
#Mann= 3 , 0 , 0
       0      .1       0   443.3    .045       0   458.3      .1       0
Bank Sta=443.3,458.3
XS Rating Curve= 0 ,0
Exp/Cntr=0.3,0.1

Type RM Length L Ch R = 1 ,22148   ,229.8,213.2,196.7
XS GIS Cut Line= 4
     1814783.758       166176.68     1814494.087       166419.63
     1814340.842      166417.761     1814219.367      166602.777
#Sta/Elev= 30
     9.9 1792.61    19.9 1795.98    39.8 1805.35    59.7 1812.73    89.5 1826.06
    99.5 1829.64   129.3 1833.94   149.2 1834.02   159.2 1831.15   169.1 1826.28
   228.8 1792.79   268.6 1772.01   298.5 1758.18   318.4 1750.28   348.2 1741.09
   358.2 1739.43   378.1 1740.14   406.8 1737.71   416.4 1736.13   447.2 1727.64
   454.7  1727.5   462.2 1728.11   483.4 1730.16     493 1732.46   561.5 1753.95
   591.7 1766.47   662.1 1807.65   712.4 1843.69   732.5 1856.02   752.7 1866.89
#Mann= 3 , 0 , 0
       0      .1       0   447.2    .045       0   462.2      .1       0
Bank Sta=447.2,462.2
XS Rating Curve= 0 ,0
Exp/Cntr=0.3,0.1

Type RM Length L Ch R = 1 ,21934.8 ,247.3,246.4,245.4
XS GIS Cut Line= 4
     1814704.347       166038.18     1814485.246      166139.423
     1814335.313      166267.956     1814119.463      166433.325
#Sta/Elev= 30
    10.1 1810.12    50.3 1797.65   110.6 1786.33   130.7 1780.57     171 1764.37
   191.1 1754.12   211.2 1745.02   221.2 1743.01   231.3 1743.11   241.4 1742.39
   251.2 1743.69   261.1 1743.69     271  1742.5     350 1718.06   359.9 1715.71
   362.2  1715.7   369.7 1715.64   377.2 1717.24   389.5 1720.26   399.4 1721.75
   469.1 1723.49   479.1 1725.53   489.2 1729.23   539.6 1749.85   559.7  1758.9
   579.8 1770.35   630.2 1802.01   660.4 1819.95   670.5 1825.26   710.8 1842.13
#Mann= 3 , 0 , 0
       0      .1       0   362.2    .045       0   377.2      .1       0
Bank Sta=362.2,377.2
XS Rating Curve= 0 ,0
Exp/Cntr=0.3,0.1

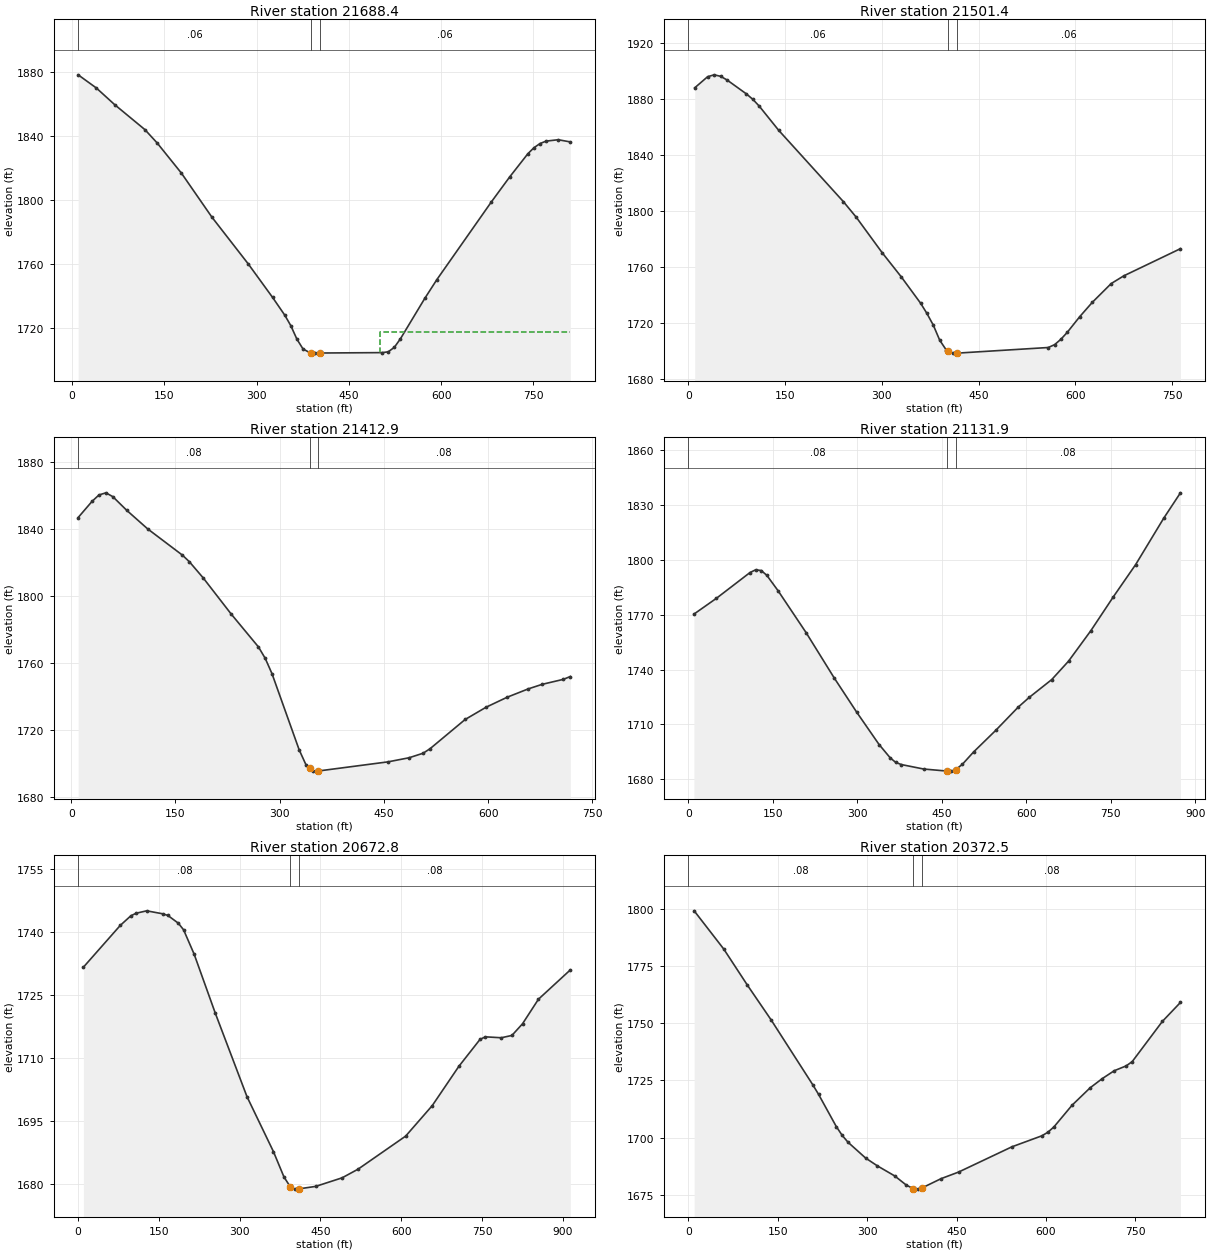
Type RM Length L Ch R = 1 ,21688.4 ,185.5,187,188.6
XS GIS Cut Line= 4
     1814530.274      165778.811     1814297.017      165977.254
     1814102.056      166160.031     1814013.278      166379.362
#Sta/Elev= 30
     9.9    1878    39.5 1869.79    69.2 1859.43   118.5 1843.82   138.3 1835.55
   177.8 1816.72   227.2 1789.37   286.5 1760.11     326 1739.26   345.8 1728.21
   355.7 1721.61   365.6  1713.2   375.5 1707.12   387.8 1704.55   395.3 1704.52
   402.8 1704.59   504.2 1704.84   514.1 1705.34     524 1708.16   533.9 1713.47
   573.5 1738.66   593.2  1750.4   681.9 1798.88   711.5 1814.35   741.1 1828.83
     751 1832.57   760.8 1835.15   770.7 1836.68   790.4 1837.54   810.1 1836.18
#Mann= 3 , 0 , 0
     9.9     .06       0   387.8    .045       0   402.8     .06       0
#XS Ineff= 2 , 0
                          500.71         1717.56
Permanent Ineff=
       F       F
Bank Sta=387.8,402.8
XS Rating Curve= 0 ,0
Exp/Cntr=0.3,0.1

Type RM Length L Ch R = 1 ,21501.4 ,96.9,88.4,80
XS GIS Cut Line= 4
     1814382.041      165607.635     1814189.092      165837.996
     1814013.175      165983.747     1813912.876      166195.368
#Sta/Elev= 30
      10 1888.06      30 1896.02    40.1 1897.37    50.1 1896.32    60.1 1893.69
    90.1 1883.73   100.2  1879.8   110.2 1874.89   140.2 1857.67   240.4 1806.68
   260.4 1795.51   300.5 1770.18   330.3 1752.77   360.1 1734.04     370 1726.65
     380 1718.17   389.9 1707.44   399.8 1700.62   402.3 1700.02   409.8 1698.23
   417.3 1698.24   558.2 1702.25     568  1704.3   577.7 1708.12   587.5 1713.03
     607 1724.34   626.5 1734.59   655.8 1748.03   675.3 1753.54   763.1 1772.97
#Mann= 3 , 0 , 0
       0     .06       0   402.3    .045       0   417.3     .06       0
Bank Sta=402.3,417.3
XS Rating Curve= 0 ,0
Exp/Cntr=0.3,0.1

Type RM Length L Ch R = 1 ,21412.9 ,292.3,281,269.7
XS GIS Cut Line= 4
     1814122.944      165524.665      1814084.81      165761.796
     1813993.574      165923.434     1813851.391      166179.178
#Sta/Elev= 30
      10 1846.87      30 1856.53      40 1860.38      50 1861.64      60 1859.32
    80.1 1851.11   110.1 1840.07   160.1 1824.38   170.1 1820.44   190.1 1810.72
   230.2 1789.21   269.5 1769.52   279.3 1762.65     289 1753.53   328.1 1708.02
   337.9 1699.07  343.13 1697.12   347.6 1695.27   355.1 1695.32   456.1 1700.82
   486.3 1703.26   506.5 1705.97   516.6  1708.7     567 1726.14   597.3 1733.51
   627.6 1739.47   657.9 1744.44     678 1747.17   708.3 1750.13   718.4 1751.82
#Mann= 3 , 0 , 0
      10     .08       0  343.13    .045       0   355.1     .08       0
Bank Sta=343.13,355.1
XS Rating Curve= 0 ,0
Exp/Cntr=0.3,0.1

Type RM Length L Ch R = 1 ,21131.9 ,430.4,459.1,487.9
XS GIS Cut Line= 4
     1813937.384      165457.589     1813759.132      165745.737
     1813755.651      165952.884     1813670.788      166269.647
#Sta/Elev= 30
      10 1770.37    49.8    1779   109.6 1793.14   119.6 1794.64   129.6 1794.24
   139.5 1791.62   159.4 1783.21   209.3 1760.22   259.1 1735.47     299 1716.74
   338.8 1699.01   358.6  1691.7   368.4 1689.21   378.3 1688.04   417.8  1685.6
   459.6 1684.46   467.1 1684.44   474.6 1685.21   486.8 1688.21   506.5 1694.89
     546 1706.77   585.8 1719.46   605.6 1724.85   645.4 1734.56   675.2 1744.63
   714.9 1761.35   754.7 1779.83   794.4 1797.52   844.1 1822.83   873.9 1836.78
#Mann= 3 , 0 , 0
       0     .08       0   459.6    .045       0   474.6     .08       0
Bank Sta=459.6,474.6
XS Rating Curve= 0 ,0
Exp/Cntr=0.3,0.1

Type RM Length L Ch R = 1 ,20672.8 ,323.8,300.3,275.8
XS GIS Cut Line= 4
      1813862.44      165414.368     1813665.133      165604.738
     1813383.135      165690.034     1813116.707      165909.546
#Sta/Elev= 30
     9.8 1731.58    78.3 1741.53    97.9 1743.81   107.7 1744.42   127.3 1744.99
   156.7 1744.29   166.5  1743.9     186 1742.05   195.8 1740.47   215.4 1734.68
   254.6 1720.66   313.5 1700.77   362.6  1687.7   382.2 1681.65   394.3 1679.23
   401.8 1678.75   409.3  1678.8   441.1  1679.4   490.2 1681.44   519.7 1683.49
   608.2 1691.37   657.6 1698.63   706.9 1707.96   746.3 1714.39   756.2    1715
   785.8 1714.78   805.5 1715.33   825.2  1718.1   854.8 1723.95     914 1730.93
#Mann= 3 , 0 , 0
       0     .08       0   394.3    .045       0   409.3     .08       0
Bank Sta=394.3,409.3
XS Rating Curve= 0 ,0
Exp/Cntr=0.3,0.1

Type RM Length L Ch R = 1 ,20372.5 ,425.6,433.5,438.9
XS GIS Cut Line= 4
     1813518.912      165183.483     1813341.358      165397.592
     1813269.988      165599.516     1813042.664      165843.292
#Sta/Elev= 30
     9.9 1799.02    59.6 1782.32    99.3 1766.55   139.1 1751.39   208.6 1723.24
   218.5 1718.98   248.3  1704.9   258.3 1701.01   268.2    1698   297.6 1691.14
   317.1 1687.77   346.3 1683.36   365.8 1679.35   377.7 1677.78   385.2  1677.6
   392.7  1678.2   424.2 1682.18   453.4 1685.04   542.8 1696.05   593.3 1700.88
   603.4 1702.45   613.5 1704.78   643.8 1714.21   674.1  1721.8   694.3 1725.79
   714.5 1729.25   734.7 1731.38   744.8 1733.27   795.3 1750.78   825.6 1759.04
#Mann= 3 , 0 , 0
       0     .08       0   377.7    .045       0   392.7     .08       0
Bank Sta=377.7,392.7
XS Rating Curve= 0 ,0
Exp/Cntr=0.3,0.1

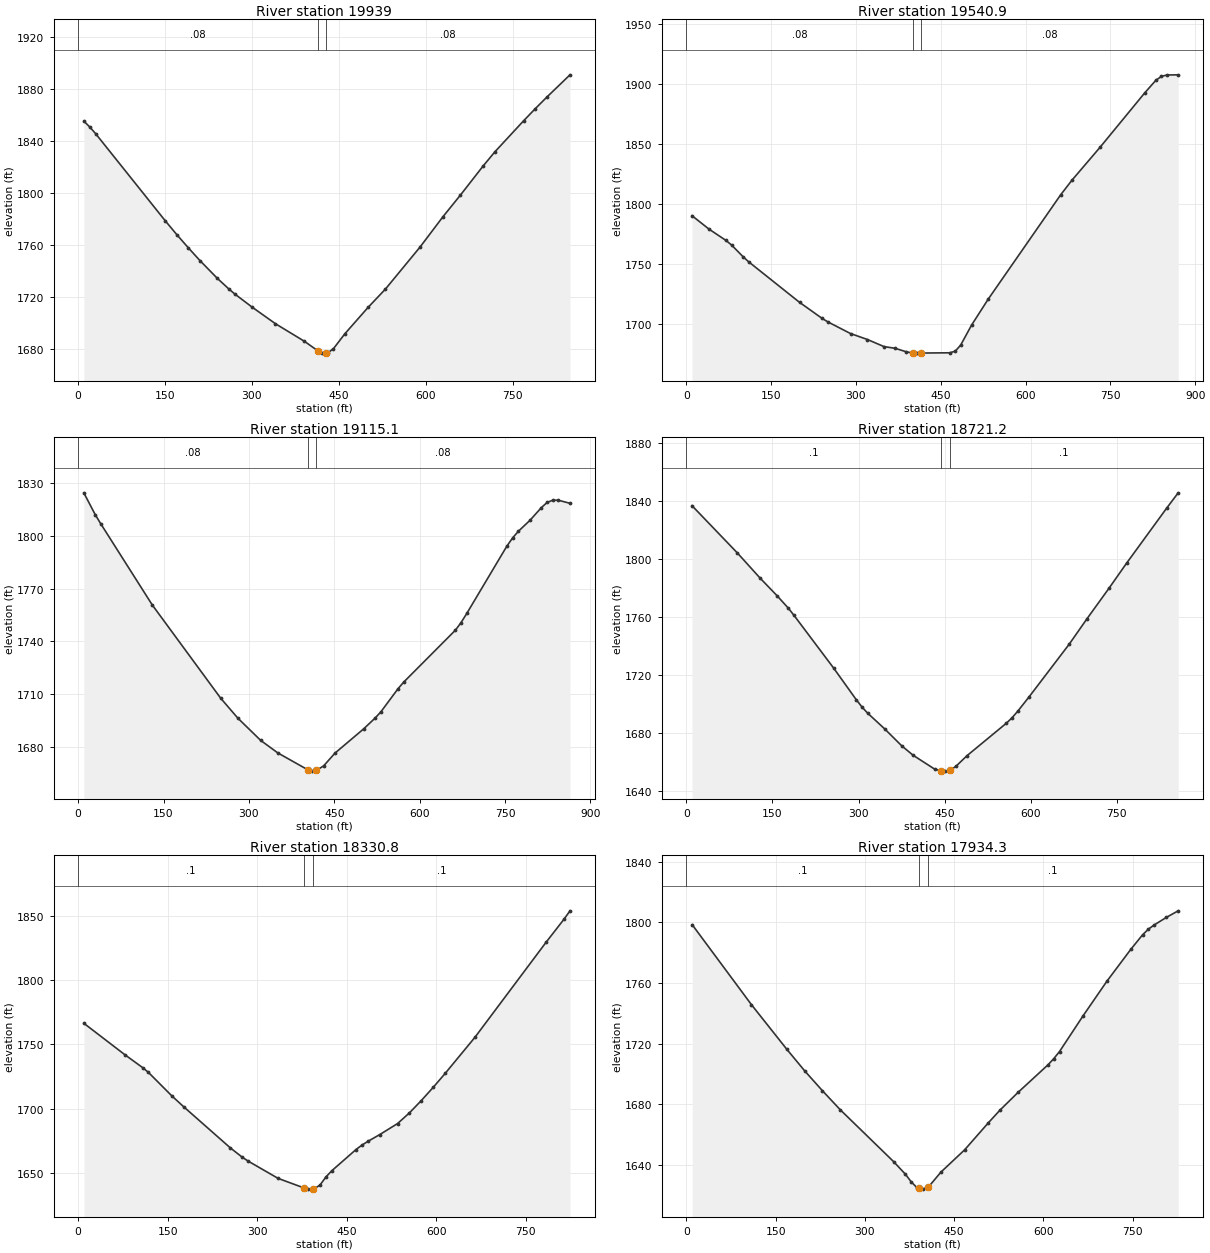
Type RM Length L Ch R = 1 ,19939   ,412.6,398.2,383.4
XS GIS Cut Line= 3
     1813258.929      165013.731     1812953.463      165317.385
     1812655.831      165611.281
#Sta/Elev= 30
      10 1855.12      20 1850.69      30 1845.65   150.2 1778.79   170.3 1768.08
   190.3 1757.91   210.3 1748.15   240.4 1734.48   260.4 1726.29   270.4 1722.52
   300.5 1712.39   340.6 1699.72   390.6 1686.22   413.2 1679.11   420.7 1677.15
   428.2 1677.22   430.7 1677.24   440.7 1680.57   460.6  1692.1   500.4 1712.21
   530.3 1726.22   590.1 1758.49   629.9 1781.91   659.8 1798.37   699.6 1821.03
   719.5 1831.68   769.3 1855.59   789.2 1864.78   809.2 1873.66     849 1890.69
#Mann= 3 , 0 , 0
       0     .08       0   413.2    .045       0   428.2     .08       0
Bank Sta=413.2,428.2
XS Rating Curve= 0 ,0
Exp/Cntr=0.3,0.1

Type RM Length L Ch R = 1 ,19540.9 ,410.6,425.7,440.9
XS GIS Cut Line= 4
     1812791.904      164719.944     1812725.696      165043.683
      1812692.52      165244.126     1812573.904      165558.941
#Sta/Elev= 30
      10 1790.23    40.1 1779.06    70.1 1769.63    80.1 1765.79   100.1  1756.2
   110.1 1751.91   200.3 1718.11   240.3 1704.72   250.3 1701.87   290.4 1692.16
   320.4 1687.19   349.8 1681.28   369.1 1679.92   388.5 1677.06   400.3 1675.92
   407.8 1675.87   415.3 1675.94   465.9 1676.15   475.6  1677.5   485.2  1682.5
   504.6 1699.23   533.6 1720.53   662.2 1807.64     682  1819.7   731.5 1846.97
   810.7 1892.34   830.5 1902.87   840.3 1906.13   850.2 1907.28     870 1907.43
#Mann= 3 , 0 , 0
       0     .08       0   400.3    .045       0   415.3     .08       0
Bank Sta=400.3,415.3
XS Rating Curve= 0 ,0
Exp/Cntr=0.3,0.1

Type RM Length L Ch R = 1 ,19115.1 ,406.5,393.9,381.3
XS GIS Cut Line= 4
     1812642.771      164642.563     1812438.974      164903.016
     1812343.045      164991.832     1812260.937      165385.994
#Sta/Elev= 30
      10 1824.61    30.1 1812.15    40.1  1806.8   130.3 1760.72   250.5 1707.61
   280.6 1696.27   320.7 1683.61   350.8 1676.47   403.7 1666.83   411.2  1666.1
   418.7 1666.54   431.3 1669.09   451.4 1676.41   501.7 1690.19   521.8 1696.34
   531.9 1699.88   562.1 1713.09   572.2 1716.88   662.8 1746.38   672.8 1750.74
   682.9 1755.97   753.3  1794.3   763.4 1798.97   773.5 1802.74   793.6 1808.89
   813.7 1816.14   823.8 1819.11   833.9 1820.42   843.9 1820.37   864.1 1818.64
#Mann= 3 , 0 , 0
       0     .08       0   403.7    .045       0   418.7     .08       0
Bank Sta=403.7,418.7
XS Rating Curve= 0 ,0
Exp/Cntr=0.3,0.1

Type RM Length L Ch R = 1 ,18721.2 ,385.9,390.4,395
XS GIS Cut Line= 4
     1812042.853      164524.507      1812060.85      164918.947
     1812030.948       165027.34     1811956.774      165368.758
#Sta/Elev= 30
     9.9 1836.78    88.8 1804.26   128.3 1786.97   157.9 1774.81   177.7 1766.16
   187.6  1761.2   256.7 1724.84   296.1 1703.05     306 1698.05   315.9 1693.83
   345.5    1683   375.1 1671.37   394.9 1664.87   432.3 1655.34   443.6 1654.14
   451.1 1653.91   458.6  1654.5   460.4 1654.64   469.8 1657.31   488.6 1664.47
   557.2 1686.85   567.2 1690.61   577.2 1695.16   597.1 1705.13     667 1741.43
     697 1758.41   736.9  1780.3   766.8 1797.16   836.7 1835.12   856.7 1845.64
#Mann= 3 , 0 , 0
       0      .1       0   443.6    .045       0   458.6      .1       0
Bank Sta=443.6,458.6
XS Rating Curve= 0 ,0
Exp/Cntr=0.3,0.1

Type RM Length L Ch R = 1 ,18330.8 ,405.2,396.5,386.2
XS GIS Cut Line= 4
     1811846.542      164486.159     1811735.925       164737.78
     1811649.704      164907.734      1811464.89      165215.107
#Sta/Elev= 30
     9.8 1766.28    78.5 1741.87     108 1731.94   117.8  1728.2   157.1 1709.91
   176.7 1701.57   255.2 1669.49   274.9 1662.35   284.9 1659.28     335 1645.88
   377.7 1638.57   385.2 1637.52   392.7  1637.6   395.2 1637.62   405.3 1640.73
   415.3 1647.03   425.3 1651.92   465.4 1668.21   475.4 1671.68   485.4  1674.6
   505.3 1679.88   535.2 1688.45   555.1 1696.76     575 1706.34     595 1716.62
   614.9 1727.38   664.7 1755.38   784.2  1829.4   814.1 1847.23   824.1 1853.72
#Mann= 3 , 0 , 0
       0      .1       0   377.7    .045       0   392.7      .1       0
Bank Sta=377.7,392.7
XS Rating Curve= 0 ,0
Exp/Cntr=0.3,0.1

Type RM Length L Ch R = 1 ,17934.3 ,259.6,263.2,268.4
XS GIS Cut Line= 3
     1811333.413      164357.006     1811299.833      164763.502
     1811301.673      165182.175
#Sta/Elev= 30
     9.9  1798.4   109.4 1745.73   169.1 1716.21     199 1702.05   228.8 1688.97
   258.7 1676.46   348.2 1642.34   368.1 1634.02     378 1628.93     388 1624.97
   390.4 1624.78   397.9 1624.16   405.4 1625.56   407.9 1626.03   427.8 1635.35
   467.7 1650.05   507.6 1667.88   527.5 1676.38   557.4 1687.88   607.3 1705.89
   617.2 1709.99   627.2 1714.85   667.1 1738.57   706.9 1761.23   746.8 1782.09
   766.7 1791.73   776.7 1795.55   786.7 1798.34   806.6 1803.21   826.6 1807.56
#Mann= 3 , 0 , 0
       0      .1       0   390.4    .045       0   405.4      .1       0
Bank Sta=390.4,405.4
XS Rating Curve= 0 ,0
Exp/Cntr=0.3,0.1