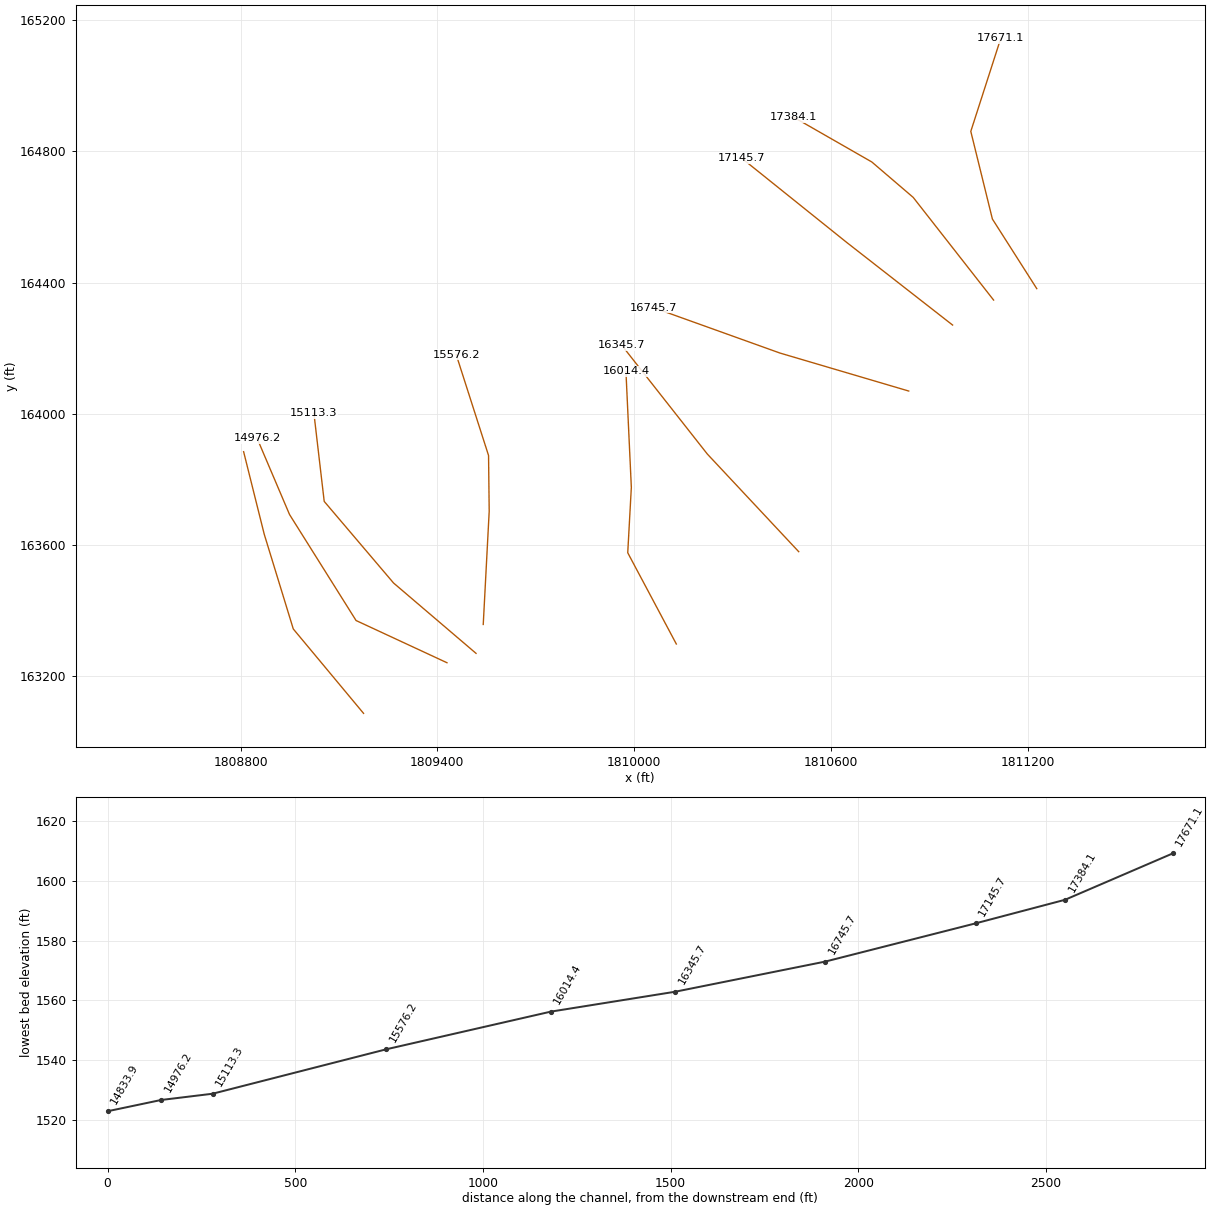
HEC-RAS study Browns Creek.prj: Browns Creek

--- Browns Creek.g01 (geometry) --- (continued)

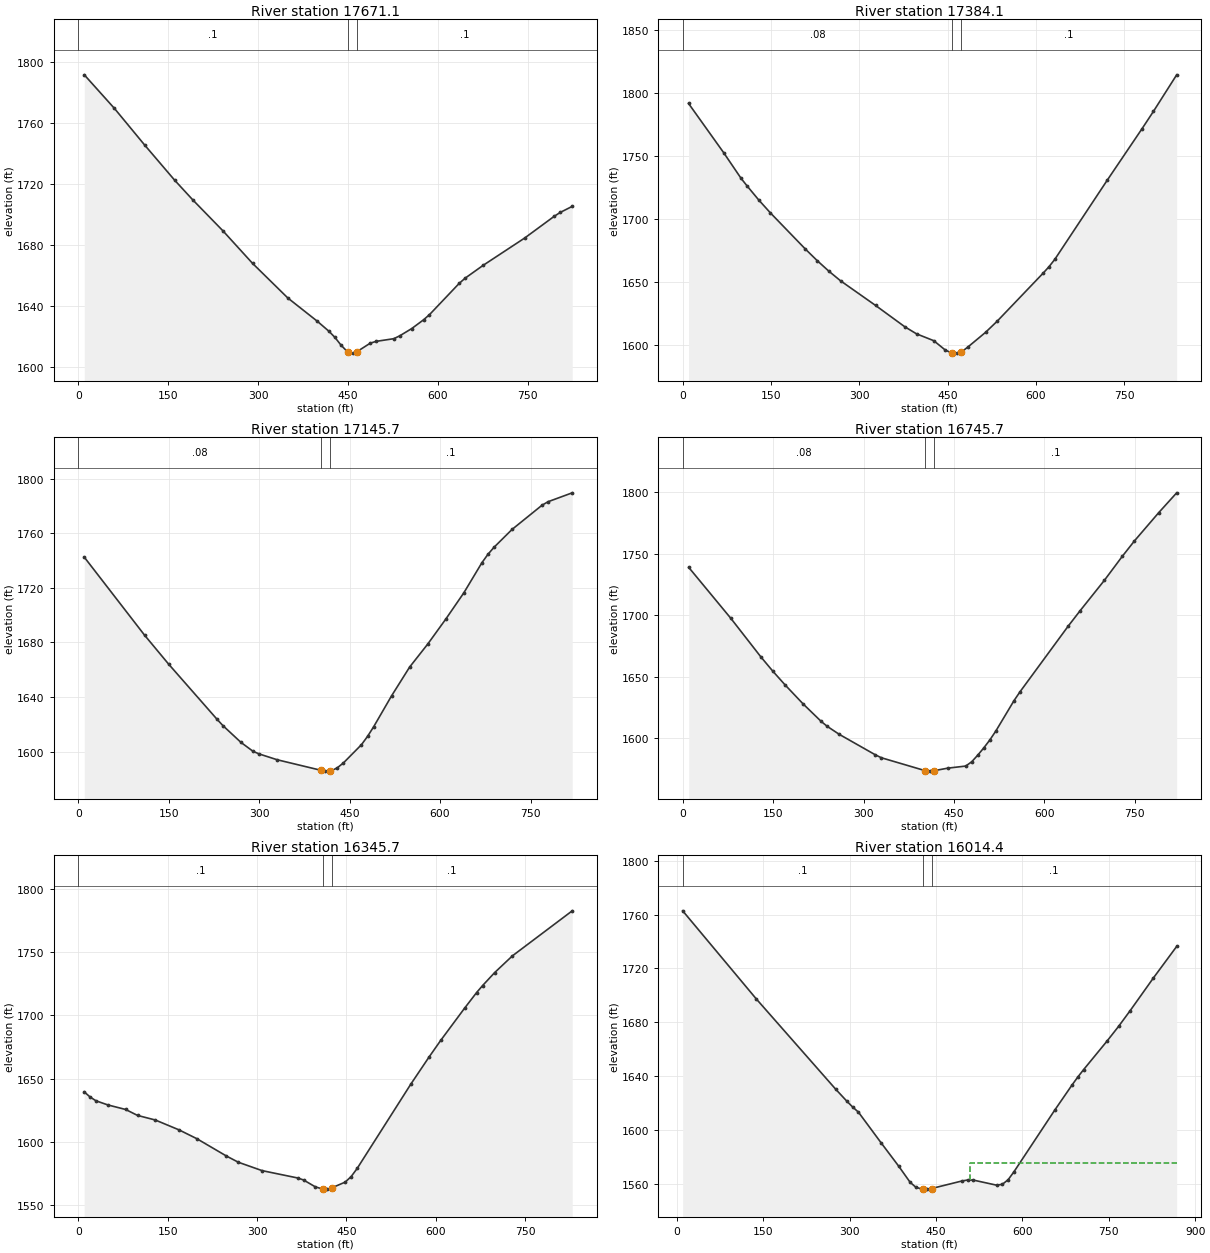
Type RM Length L Ch R = 1 ,17671.1 ,270.3,287,302.4
XS GIS Cut Line= 4
     1811227.709      164381.456      1811092.39      164593.578
     1811026.559       164860.56     1811117.991         165144.
#Sta/Elev= 30
    10.1 1791.56    60.4 1769.54   110.7 1745.61     161 1722.45   191.2 1709.58
   241.5  1689.3   290.9 1667.98   349.8 1645.28   398.9 1630.07   418.6 1623.41
   428.4 1619.44   438.2 1614.56     448 1610.53   450.3 1610.21   457.8 1609.15
   465.3 1610.14   487.3 1615.67   497.1 1616.86   526.6 1618.61   536.5 1620.48
   556.4 1625.21   576.2 1630.96   586.2 1634.38   635.8 1654.88   645.7 1658.29
   675.5 1666.63     745 1684.58   794.6  1698.9   804.6 1701.41   824.4 1705.34
#Mann= 3 , 0 , 0
       0      .1       0   450.3    .045       0   465.3      .1       0
Bank Sta=450.3,465.3
XS Rating Curve= 0 ,0
Exp/Cntr=0.3,0.1

Type RM Length L Ch R = 1 ,17384.1 ,237.4,238.4,239.1
XS GIS Cut Line= 4
     1811096.047      164346.712     1810851.009       164659.41
     1810724.833        164767.3      1810485.28      164904.448
#Sta/Elev= 30
     9.9 1791.59    69.5 1752.62    99.3 1732.12   109.2  1726.3   129.1 1715.11
     149 1704.82   208.6 1676.06   228.4 1667.03   248.3 1658.62   268.2 1650.98
   327.7 1631.45   377.4 1614.52   397.3 1608.93   426.6 1603.49   446.1  1596.1
   455.9    1594   458.1 1593.91   465.6 1593.64   473.1 1594.81   475.4 1595.17
   485.2 1598.73   514.5 1610.08     534 1618.79   612.6 1657.13   622.4 1662.15
   632.3 1668.01     721  1730.5   780.2 1771.37   799.9 1785.33   839.3 1814.25
#Mann= 3 , 0 , 0
       0     .08       0   458.1    .045       0   473.1      .1       0
Bank Sta=458.1,473.1
XS Rating Curve= 0 ,0
Exp/Cntr=0.3,0.1

Type RM Length L Ch R = 1 ,17145.7 ,391.5,400,407.5
XS GIS Cut Line= 3
     1810971.091      164270.539     1810647.894      164522.499
     1810328.435       164778.57
#Sta/Elev= 30
      10 1742.42   109.9 1685.35   149.9 1664.09   229.9 1623.85   239.9 1619.08
   269.9 1606.77   289.9 1600.26   299.9 1598.35   329.8 1594.09   402.3 1586.38
   409.8 1585.75   417.3 1585.91   419.8 1585.96   429.8 1588.25   439.8 1591.78
   469.7 1605.12   479.7 1611.16   489.7 1618.08   519.6 1640.87   549.6 1661.97
   579.6  1678.8   609.5 1697.06   639.5 1716.34   669.4 1738.34   679.4 1744.48
   689.4  1749.6   719.4 1762.72   769.3 1780.51   779.3 1783.04   819.2 1789.52
#Mann= 3 , 0 , 0
       0     .08       0   402.3    .045       0   417.3      .1       0
Bank Sta=402.3,417.3
XS Rating Curve= 0 ,0
Exp/Cntr=0.3,0.1

Type RM Length L Ch R = 1 ,16745.7 ,411.9,400,387.4
XS GIS Cut Line= 3
     1810837.338      164069.514     1810444.449      164185.343
     1810058.603      164323.653
#Sta/Elev= 30
      10 1738.88    79.9 1697.37   129.9 1665.86   149.9 1654.15   169.8 1643.22
   199.8 1627.69   229.8 1613.44   239.8 1609.43   259.8 1602.91   319.7 1586.23
   329.7 1583.85   402.1 1573.38   409.6 1572.98   417.1 1573.33   439.6 1575.39
   469.6 1577.11   479.6 1580.65   489.6 1586.06   499.6 1591.95   509.6  1598.4
   519.6 1605.72   549.6 1630.33   559.6 1637.58   639.5 1691.02   659.5 1703.71
   699.5 1728.29   729.5 1748.01   749.5 1760.46   789.5 1783.31   819.5 1799.57
#Mann= 3 , 0 , 0
       0     .08       0   402.1    .045       0   417.1      .1       0
Bank Sta=402.1,417.1
XS Rating Curve= 0 ,0
Exp/Cntr=0.3,0.1

Type RM Length L Ch R = 1 ,16345.7 ,349.7,331.4,315.1
XS GIS Cut Line= 3
     1810501.846      163580.174      1810223.06      163877.832
     1809962.596      164208.682
#Sta/Elev= 30
     9.9 1639.69    19.9 1635.58    29.8 1632.58    49.7 1629.33    79.6 1625.73
    99.5 1621.05   129.3 1617.44   169.1 1609.65   198.9 1602.72   248.7    1589
   268.6 1584.11   308.4  1577.5     368 1571.71     378 1570.12   397.9 1564.67
   410.4 1562.94   417.9 1562.89   425.4 1563.89   447.9 1568.42     458 1572.83
     468  1579.2   558.2 1645.85   588.3 1666.89   608.3 1680.32   648.4 1705.75
   668.5 1718.04   678.5 1723.52   698.6  1733.7   728.6 1746.99   828.9  1782.5
#Mann= 3 , 0 , 0
       0      .1       0   410.4    .045       0   425.4      .1       0
Bank Sta=410.4,425.4
XS Rating Curve= 0 ,0
Exp/Cntr=0.3,0.1

Type RM Length L Ch R = 1 ,16014.4 ,436.7,438.2,439.7
XS GIS Cut Line= 4
     1810128.695      163298.899     1809980.575      163576.853
     1809991.547      163776.175     1809975.089      164129.103
#Sta/Elev= 30
     9.8 1762.78   137.8 1697.32   275.6 1630.38   295.3 1621.34   305.1 1617.15
     315  1613.4   354.9 1590.35   384.8  1573.4   404.8 1561.35   414.8 1557.63
   424.8 1556.33   427.2 1556.31   434.7 1556.23   442.2 1556.69   494.6 1562.25
   504.6 1562.98   514.6 1562.95     555 1559.17   565.1 1559.81   575.1 1563.21
   585.2 1569.08   655.9 1614.75   686.2 1633.56   696.3 1639.51   706.4 1645.01
   746.8 1666.04   766.9 1676.97   787.1  1688.7   827.5 1712.98   867.9 1736.37
#Mann= 3 , 0 , 0
     9.8      .1       0   427.2    .045       0   442.2      .1       0
#XS Ineff= 2 , 0
                          508.69         1575.76
Permanent Ineff=
       F       F
Bank Sta=427.2,442.2
XS Rating Curve= 0 ,0
Exp/Cntr=0.3,0.1

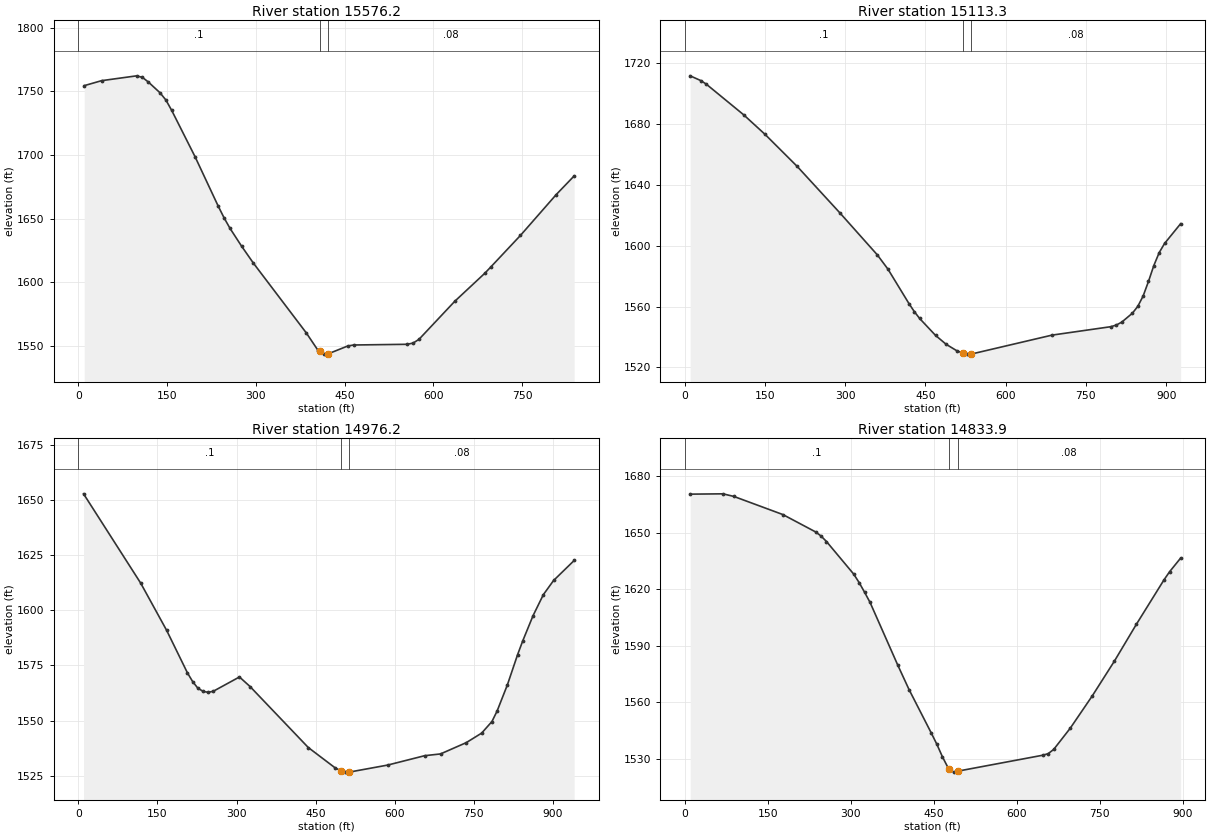
Type RM Length L Ch R = 1 ,15576.2 ,447.1,462.9,478.6
XS GIS Cut Line= 4
     1809539.986      163358.448     1809558.158      163703.029
     1809556.209      163873.113     1809457.583      164180.305
#Sta/Elev= 30
     9.9 1754.46    39.4 1758.39    98.6 1762.18   108.4 1760.93   118.3 1757.32
     138 1748.88   147.9 1743.23   157.7 1735.09   197.2 1698.68   236.6 1659.62
   246.5 1650.46   256.3  1642.4     276 1628.31   295.8  1615.1   385.1 1560.37
   405.1 1546.52   407.6  1545.8   415.1 1543.64   422.6 1543.96   455.1    1550
   465.1 1550.81   555.5 1551.36   565.6 1552.31   575.6 1555.25   636.1 1585.15
   686.6 1607.04   696.6 1611.91     747 1636.83   807.5 1668.93   837.8 1683.57
#Mann= 3 , 0 , 0
       0      .1       0   407.6    .045       0   422.6     .08       0
Bank Sta=407.6,422.6
XS Rating Curve= 0 ,0
Exp/Cntr=0.3,0.1

Type RM Length L Ch R = 1 ,15113.3 ,140.2,137.1,134
XS GIS Cut Line= 4
     1809517.985      163270.441     1809266.547      163484.735
      1809055.11      163733.316      1809023.68      164001.898
#Sta/Elev= 30
      10 1711.75      30 1708.61      40 1706.33   110.1 1686.12   150.2 1673.21
   210.2 1652.18   290.3 1621.51     360 1594.02   379.8 1584.68   419.4 1561.86
   429.3 1556.65   439.1 1552.22   468.8 1541.11   488.6 1535.25   508.4 1531.03
   520.7 1529.33   528.2 1528.77   535.7 1528.82   686.8 1541.28   796.9 1546.82
   806.9  1547.9     817  1549.8     837  1555.7     847 1560.18     857 1566.97
     867 1576.58     877 1587.01   887.1 1595.57   897.1 1601.54   927.1 1614.52
#Mann= 3 , 0 , 0
       0      .1       0   520.7    .045       0   535.7     .08       0
Bank Sta=520.7,535.7
XS Rating Curve= 0 ,0
Exp/Cntr=0.3,0.1

Type RM Length L Ch R = 1 ,14976.2 ,148.2,142.3,136.3
XS GIS Cut Line= 4
      1809429.41      163241.868     1809152.256      163370.445
     1808949.391      163693.315     1808850.111      163926.442
#Sta/Elev= 30
     9.9 1652.68   118.3 1612.23   167.5 1590.85     207 1571.56   216.8 1567.67
   226.7 1564.67   236.5 1563.27   246.4 1562.79   256.2 1563.33   305.5 1569.76
   325.6 1565.44     436 1537.83   486.1 1528.77   498.7 1527.13   506.2 1526.68
   513.7 1526.69   586.5 1529.87   656.7 1534.12   686.8 1534.92   735.6 1540.03
   764.8 1544.35   784.3 1549.59     794 1554.29   813.5 1566.13     833  1579.9
   842.8 1586.16   862.3 1597.54   881.8 1607.04   901.2 1613.45   940.2  1622.5
#Mann= 3 , 0 , 0
       0      .1       0   498.7    .045       0   513.7     .08       0
Bank Sta=498.7,513.7
XS Rating Curve= 0 ,0
Exp/Cntr=0.3,0.1

Type RM Length L Ch R = 1 ,14833.9 ,14853.8,14833.9,14814.1
XS GIS Cut Line= 4
     1809175.115      163087.576      1808960.82      163344.729
     1808872.245      163633.312     1808809.386      163884.751
#Sta/Elev= 30
     9.8 1670.53    68.9  1670.7    88.6 1669.32   177.2 1659.69   236.3 1650.48
   246.1 1648.31     256 1645.37   305.2 1628.06     315 1623.56   324.9 1618.39
   334.7 1613.04     385 1579.59   405.2 1566.73   445.4 1543.64   455.5 1537.64
   465.5 1531.03   475.6 1525.27   478.2 1524.66   485.7 1522.92   493.2 1523.44
   646.6 1531.89   656.5 1532.73   666.5 1534.98   696.4 1546.25   736.3 1563.46
   776.2 1581.89     816 1601.49   865.9 1625.08   875.8 1629.31   895.8 1636.57
#Mann= 3 , 0 , 0
       0      .1       0   478.2    .045       0   493.2     .08       0
Bank Sta=478.2,493.2
XS Rating Curve= 0 ,0
Exp/Cntr=0.3,0.1

Chan Stop Cuts=-1
Use User Specified Reach Order=0